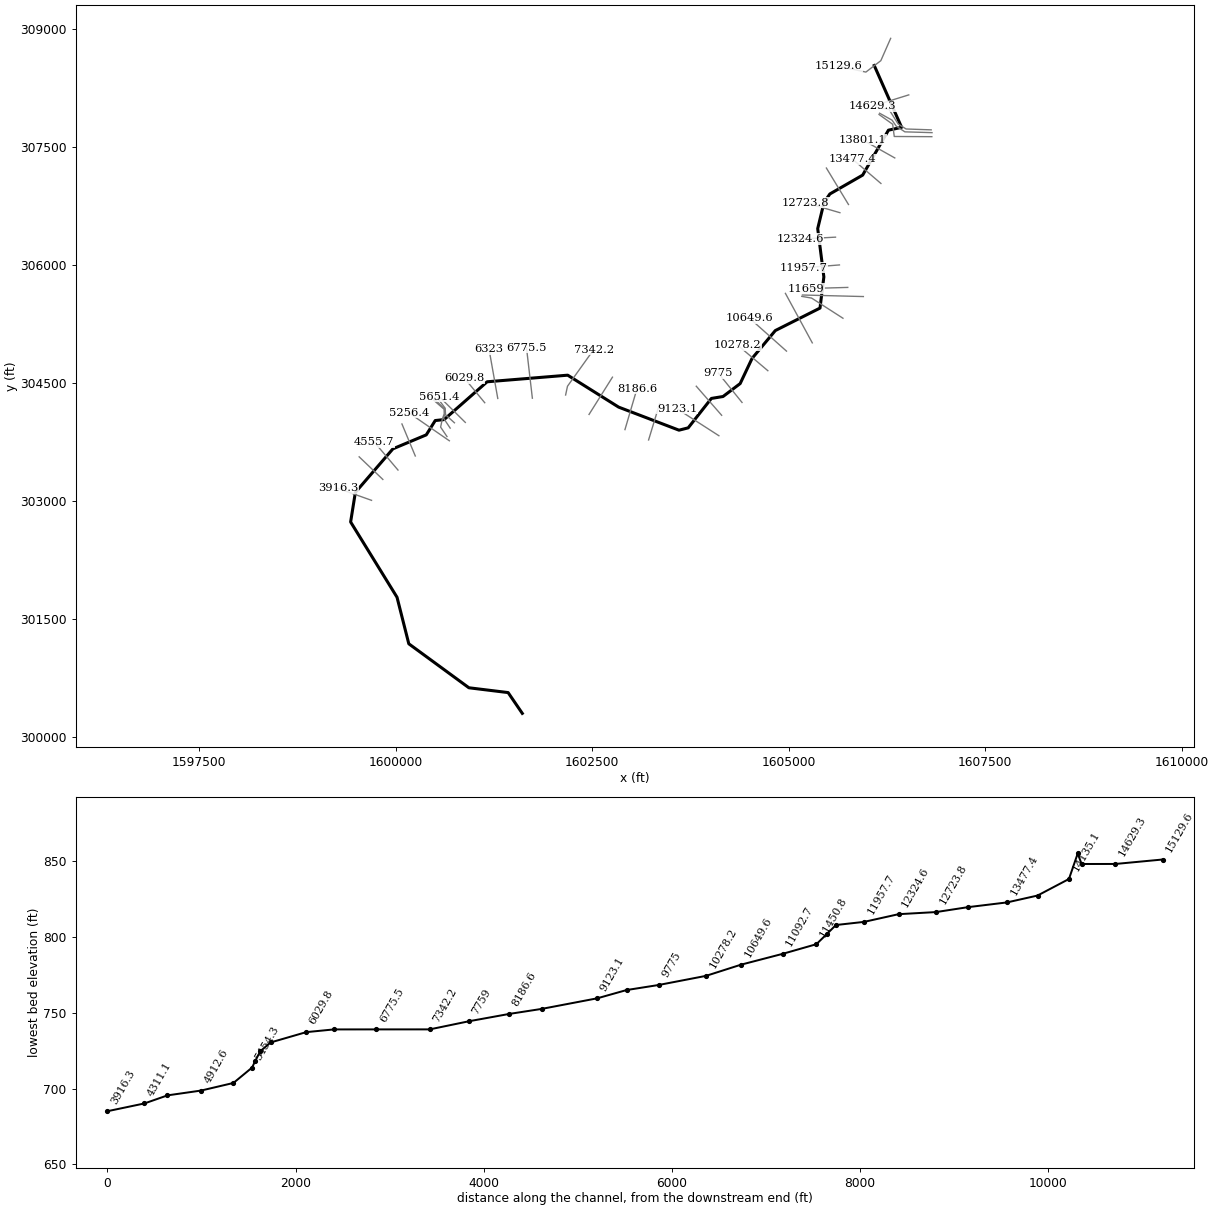
--- sprcfrk.prj (project) ---

Proj Title=sprcfrk
Current Plan=p01
Default Exp/Contr=0,0
English Units
Geom File=g01
Flow File=f01
Plan File=p01
BEGIN DESCRIPTION:
END DESCRIPTION:
DSS File=dss
DSS Export Rating Curves= 0
DSS Export Rating Curve Sorted= 0
DSS Export Volume Flow Curves= 0
DXF OffsetX= 0
DXF OffsetY= 0
DXF ScaleX= 0
DXF ScaleY= 0

--- sprcfrk.p01 (plan) ---

Plan Title=Floodplain
Program Version=4.00
Short Identifier=Floodplain
Geom File=g01
Flow File=f01
Subcritical Flow
K Sum by GR= 0
Std Step Tol= 0.01
Critical Tol= 0.01
Num of Std Step Trials= 20
Max Error Tol= 0.3
Flow Tol Ratio= 0.001
Split Flow NTrial= 30
Split Flow Tol= 0.02
Split Flow Ratio= 0.02
Log Output Level= 0
Friction Slope Method= 1
Unsteady Friction Slope Method= 2
Unsteady Bridges Friction Slope Method= 1
Parabolic Critical Depth
Global Vel Dist= 0 , 0 , 0
Global Log Level= 0
CheckData=True
Encroach Param=-1 ,0,0, 0
Run HTab= 0
Run UNet= 0
Run PostProcess= 0
Run WQNet= 0
UNET Theta= 0
UNET Theta Warmup= 0
UNET ZTol= 0
UNET ZSATol= 0
UNET MxIter= 0
UNET MaxInSteps= 0
UNET DtIC= 0
UNET DtMin= 0
UNET MaxCRTS= 0
UNET WFStab= 0
UNET SFStab= 0
UNET WFX= 1
UNET SFX= 1
UNET DSS MLevel= 1
UNET DZMax Abort= 0
UNET Convert EG Bridges= 0
UNET Use Existing IB Tables= 0
UNET Froude Reduction=False
UNET Froude Limit= 0
UNET Froude Power= 0
UNET Time Slicing=0,0, 5
DSS File=dss
Write IC File= 0
Echo Input=False
Echo Output=False
Write Detailed= 0
Detailed Automatic Start=False, 0
WQ ULTIMATE=-1
WQ Max Comp Step=1HOUR
WQ Output Interval=15MIN
WQ Output Selected Increments= 0
WQ Output face flow=0
WQ Output face velocity=0
WQ Output face area=0
WQ Output face dispersion=0
WQ Output cell volume=0
WQ Output cell surface area=0
WQ Output cell continuity=0
WQ Output face conc=0
WQ Output face dconc_dx=0
WQ Output face courant=0
WQ Output face peclet=0
WQ Output face adv mass=0
WQ Output face disp mass=0
WQ Output cell mass=0
WQ Output cell source sink temp=0
WQ Output cell source sink nsm=0
WQ Output MaxMinRange=-1
WQ Daily Max Min Mean=-1
WQ Daily Range=0
WQ Daily Time=0
WQ Create Restart=0
WQ Fixed Restart=0
WQ System Summary=False
Sorting and Armoring Iterations= 10
XS Update Threshold= 0.02
Hydraulics Update Threshold= 0.02
Energy Slope Method= 1
Volume Change Method= 0
XS Weighting Method= 0
Number of US Weighted Cross Sections= 1
Number of DS Weighted Cross Sections= 1
Upstream XS Weight=0.25
Main XS Weight=0.5
Downstream XS Weight=0.25
Number of DS XS's Weighted with US Boundary= 1
Upstream Boundary Weight= 1
Weight of XSs Associated with US Boundary= 0
Number of US XS's Weighted with DS Boundary= 1
Downstream Boundary Weight= 0.5
Weight of XSs Associated with DS Boundary= 0.5
Sediment Output Level= 4
Mass or Volume Output= 0
Output Increment Type= 1
Profile and TS Output Increment= 10
XS Output Flag= 0
XS Output Increment= 10
Disregard all LS=0
Disregard all Conn=0
Disregard all Breaches=0
Disregard all Pumps=0

--- sprcfrk.f01 (steady flow) ---

Flow Title=NFF Regression Equation
Program Version=4.00
Number of Profiles= 1
Profile Names=P100yr
River Rch & RM=sprcfrk,Main            ,15129.6
     422
River Rch & RM=sprcfrk,Main            ,14629.3
     427
River Rch & RM=sprcfrk,Main            ,13801.1
     474
River Rch & RM=sprcfrk,Main            ,11092.7
     526
River Rch & RM=sprcfrk,Main            ,9433.7
     570
River Rch & RM=sprcfrk,Main            ,6775.5
     633
River Rch & RM=sprcfrk,Main            ,3471.6
     687
River Rch & RM=sprcfrk,Main            ,3120.3
    1237
River Rch & RM=sprcfrk,Main            ,134.2
    1279
Boundary for River Rch & Prof#=sprcfrk,Main            , 1
Up Type= 0
Dn Type= 3
Dn Slope=0.012
DSS Import GetInterval= 0
DSS Import GetPeak= 0
DSS Import FillOption= 0

--- sprcfrk.g01 (geometry) ---

Geom Title=USGS 10m DEM
Program Version=4.00

River Reach=sprcfrk         ,Main
Reach XY= 30
     1606088.266      308539.099     1606436.364      307752.243
     1606268.749      307716.296      1605940.69      307144.447
     1605523.238      306904.511     1605448.855      306796.244
     1605368.619      306463.646     1605446.827      305848.851
     1605397.942      305452.358     1604829.052      305166.137
     1604533.381      304812.051     1604381.774      304491.414
     1604163.723      304326.927      1604015.27      304302.454
     1603720.514      303928.156     1603603.316      303898.436
     1602835.106      304191.919      1602186.94      304598.359
     1601161.524      304514.294     1600613.906      304033.249
     1600501.304      304021.122     1600387.039      303838.756
     1599962.544      303660.965     1599484.537      303106.178
     1599424.482      302730.303      1600014.89      301772.156
     1600164.805      301180.004     1600929.672      300620.243
     1601428.755      300559.124     1601609.203      300294.449

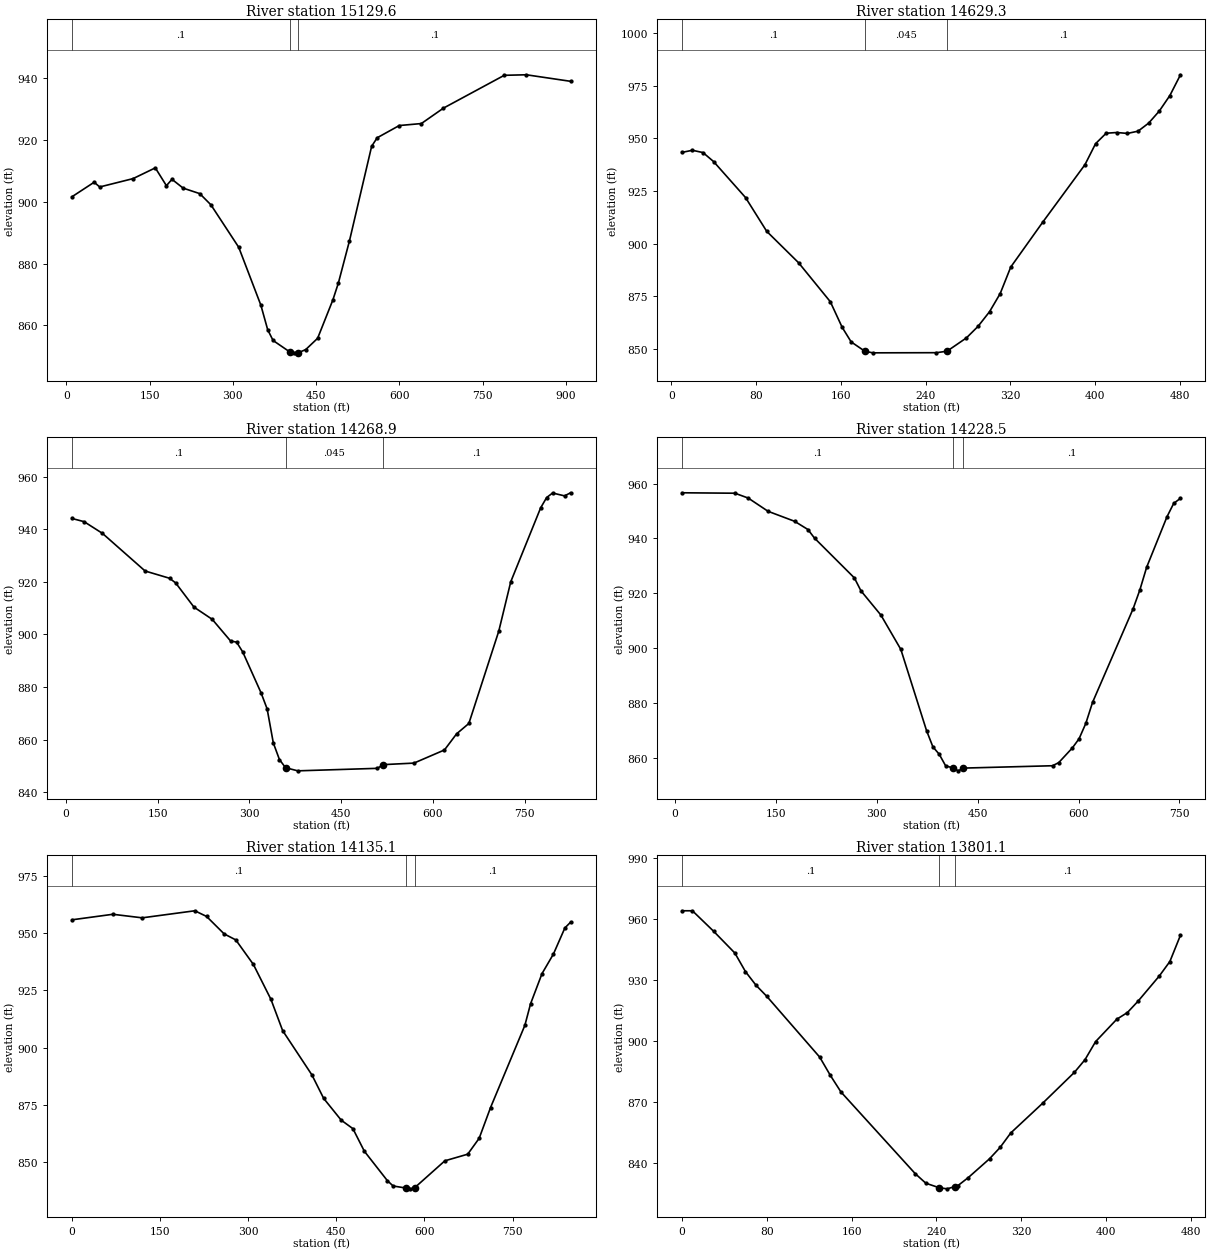
Type RM Length L Ch R = 1 ,15129.6 ,508.9,500.3,498.3
XS GIS Cut Line= 4
     1606297.157      308885.128     1606172.025      308600.893
     1605981.508      308455.646     1605631.181      308531.536
#Sta/Elev= 30
      10  901.56    50.1  906.26    60.1  904.73   120.2  907.43   160.3   910.9
   180.3  905.14   190.3  907.21   210.4  904.36   240.4  902.58   260.5  898.96
   310.6  885.26   350.5  866.56  362.79  858.64  372.51  855.16   402.9  851.43
   410.4  851.17   417.9  851.21  431.33  852.22  452.78  855.87   480.3  868.28
   490.2  873.73   510.2  887.37   550.1  917.86   560.1  920.62   599.9  924.57
   639.7  925.21   679.6   930.2   789.1  940.79   828.9  940.96   908.6  938.85
#Mann= 3 , 0 , 0
      10      .1       0   402.9    .045       0   417.9      .1       0
Bank Sta=402.9,417.9
XS Rating Curve= 0 ,0
Exp/Cntr=0.3,0.1

Type RM Length L Ch R = 1 ,14629.3 ,381.2,360.5,339.7
XS GIS Cut Line= 2
     1606527.451      308165.414     1606068.658      308022.948
#Sta/Elev= 30
      10  943.35      20  944.37      30  943.28      40     939    70.1  921.94
    90.1   905.9   120.1  891.02   150.1  872.49  161.23  860.38  169.74  853.43
   182.7  848.99   190.2  848.24   250.2  848.31   260.2  849.02  278.47  855.33
  289.41  860.79   300.3  867.77   310.3  876.34   320.3  888.96   350.3  910.14
   390.3  937.54   400.3   947.5   410.3  952.47   420.4   952.8   430.4  952.37
   440.4  953.44   450.4  957.27   460.4  962.98   470.4  970.36   480.4   980.2
#Mann= 3 , 0 , 0
      10      .1       0   182.7    .045       0   260.2      .1       0
Bank Sta=182.7,260.2
XS Rating Curve= 0 ,0
Exp/Cntr=0.3,0.1

Type RM Length L Ch R = 1 ,14268.9 ,40.7,40.4,40.2
XS GIS Cut Line= 5
     1606812.823      307720.531     1606493.776      307731.393
     1606391.952      307795.202     1606275.194        307981.2
     1606110.919      308006.995
#Sta/Elev= 30
      10  944.07    29.9  942.85    59.9  938.41   129.7  924.11   169.6  921.36
   179.6  919.59   209.5  910.41   239.4  905.76   269.4  897.54   279.3  897.09
   289.3  893.36   319.2  877.87   329.2  871.73   339.3  858.81   349.3   852.5
   359.3  849.41   379.3  848.22   509.3  849.17   519.3  850.58   569.2  851.16
   619.1  856.15     639  862.29     659  866.21   707.9  901.27   727.5  920.03
   776.4  948.11   786.2  952.02   795.9  953.73   815.5  952.64   825.3  953.82
#Mann= 3 , 0 , 0
      10      .1       0   359.3    .045       0   519.3      .1       0
Bank Sta=359.3,519.3
XS Rating Curve= 0 ,0
Exp/Cntr=0.3,0.1

Type RM Length L Ch R = 1 ,14228.5 ,113.7,93.4,73
XS GIS Cut Line= 5
     1606823.404      307684.875     1606478.007      307695.033
     1606367.514      307768.049     1606314.566      307844.078
     1606156.314       307932.07
#Sta/Elev= 30
     9.9  956.68    88.9  956.52   108.6  954.76   138.2  949.92   177.7  946.27
   197.5  943.27   207.3  940.13   266.6  925.61   276.4  920.89   306.1  912.03
   335.7  899.52   373.9  869.92   383.4  863.95   392.8  861.26   402.3  857.05
   413.7   856.2   421.2   855.2   428.7   856.2   561.4  857.06   570.6   858.2
   590.8  863.55   600.8  866.89   610.9  872.53   620.9  880.19   681.3  914.38
   691.3  921.25   701.4  929.52   731.6  947.91   741.6   952.8   751.7  954.67
#Mann= 3 , 0 , 0
     9.9      .1       0   413.7    .045       0   428.7      .1       0
Bank Sta=413.7,428.7
XS Rating Curve= 0 ,0
Exp/Cntr=0.3,0.1

Type RM Length L Ch R = 1 ,14135.1 ,311.8,333.9,356
XS GIS Cut Line= 4
     1606820.969      307633.642     1606342.695      307636.025
     1606322.809      307791.289     1606148.933      307916.033
#Sta/Elev= 30
       0  955.81    69.7  958.23   119.6  956.68   209.2  959.76   229.2  957.29
   259.1  949.67     279  947.03   308.9  936.32   338.8  921.06   358.7  907.42
   408.5  888.08   428.5  877.83   458.4  868.31   478.3   864.6   497.8  854.73
     537  841.88   546.8  839.56   568.6  838.67   576.1  838.32   583.6  838.85
   634.8  850.56   673.7  853.45   693.2  860.39   712.6  873.84     771  909.73
   780.7  919.15   800.2  932.33   819.6  940.86   839.1  952.27   848.8  954.77
#Mann= 3 , 0 , 0
       0      .1       0   568.6    .045       0   583.6      .1       0
Bank Sta=568.6,583.6
XS Rating Curve= 0 ,0
Exp/Cntr=0.3,0.1

Type RM Length L Ch R = 1 ,13801.1 ,328.3,323.8,319.3
XS GIS Cut Line= 2
      1606349.33      307363.182     1605939.595      307593.446
#Sta/Elev= 30
       0  964.08      10  964.08      30     954      50   943.3      60  934.17
      70  927.43      80  922.07     130  892.12     140  883.15     150  875.01
     220  834.85     230  830.15   242.5  827.95     250  827.39   257.5  828.51
     260  828.88     270  832.92     290  842.15     300  847.75     310  854.84
     340  869.43     370  884.64     380  890.87     390  899.77     410  910.78
     420  914.06     430  919.63     450     932     460  939.14     470  952.08
#Mann= 3 , 0 , 0
       0      .1       0   242.5    .045       0   257.5      .1       0
Bank Sta=242.5,257.5
XS Rating Curve= 0 ,0
Exp/Cntr=0.3,0.1

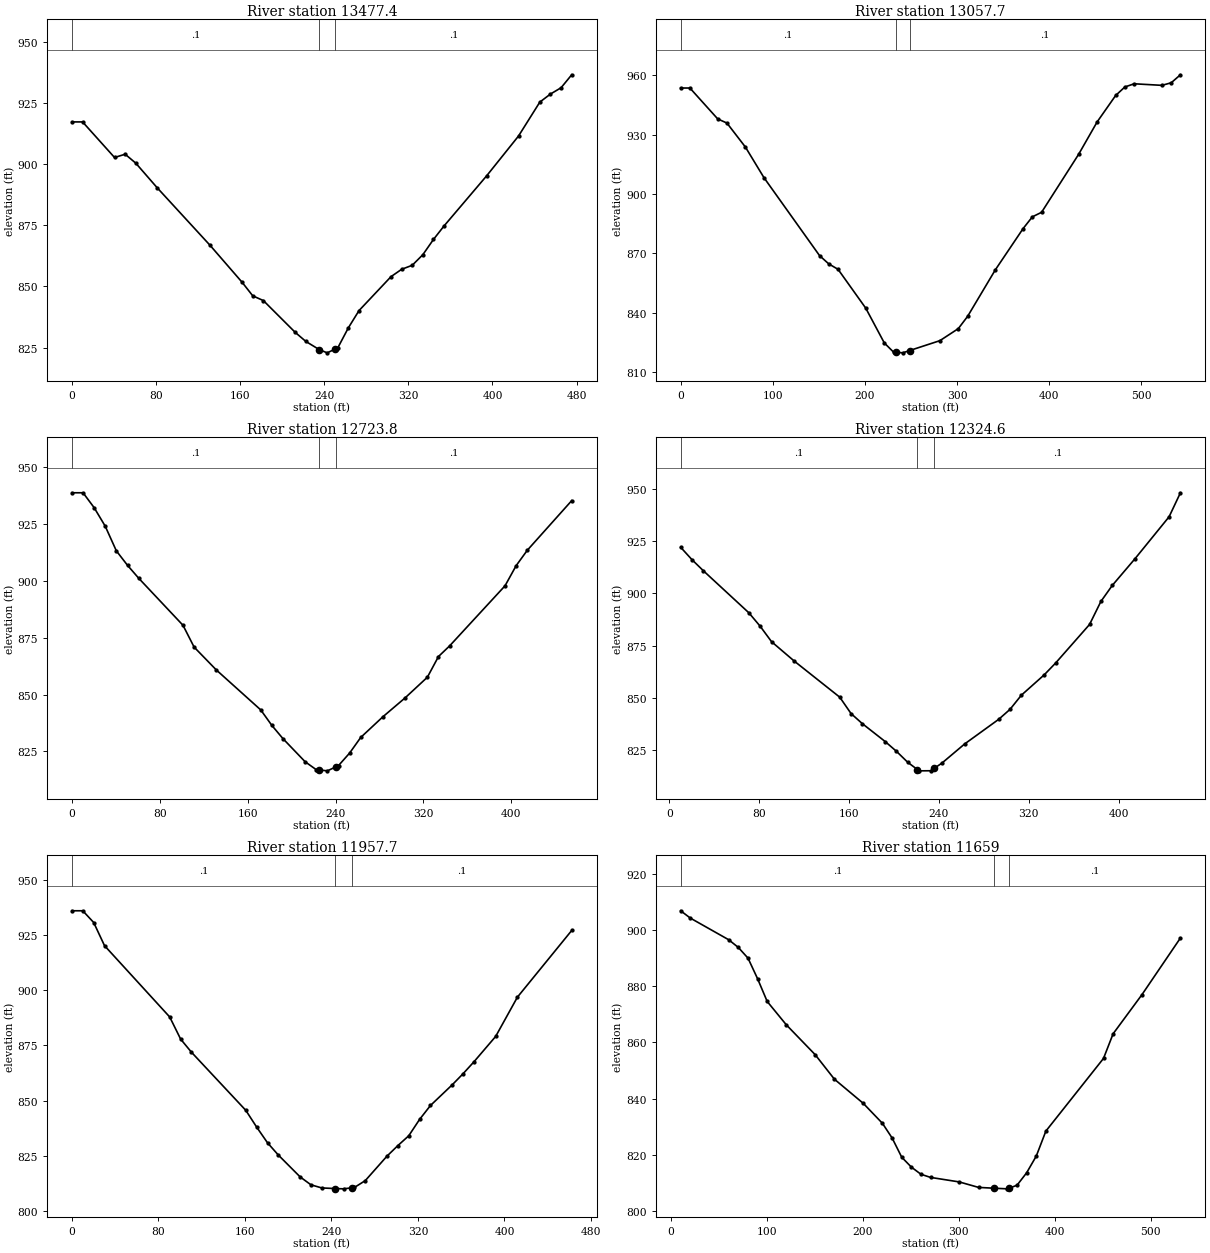
Type RM Length L Ch R = 1 ,13477.4 ,426.8,419.7,412.5
XS GIS Cut Line= 2
     1606173.246      307038.102     1605812.116       307347.31
#Sta/Elev= 30
       0  917.23    10.1  917.23    40.5  902.69    50.6  904.03    60.7  900.38
    80.9   890.4   131.5  866.74   161.8  851.73     172  846.16   182.1  844.22
   212.4  831.23   222.5  827.53   235.3  824.18   242.8  822.87   250.3   824.4
   252.9  824.93     263  833.15   273.1  840.15   303.5     854   313.6     857
   323.7  858.65   333.8  862.98   343.9  869.21     354  874.74   394.5  895.21
   424.8  911.46   445.1  925.34   455.2  928.62   465.3   931.2   475.4  936.49
#Mann= 3 , 0 , 0
       0      .1       0   235.3    .045       0   250.3      .1       0
Bank Sta=235.3,250.3
XS Rating Curve= 0 ,0
Exp/Cntr=0.3,0.1

Type RM Length L Ch R = 1 ,13057.7 ,317,333.9,350.7
XS GIS Cut Line= 2
     1605760.124      306770.589     1605479.066      307234.504
#Sta/Elev= 30
       0  953.52      10  953.52    40.2   937.9    50.2  935.81    70.3  923.65
    90.4  908.21   150.7  868.84   160.7  864.65   170.8   861.9   200.9  842.25
     221   824.7     231  820.08   233.6  819.98   241.1   819.7   248.6  820.88
   281.3  825.85   301.3  831.93   311.4  838.12   341.5  861.64   371.7  882.53
   381.7  888.43   391.7  890.72   431.9  920.01     452  936.39   472.1  949.75
   482.1  954.05   492.2  955.66   522.3  954.87   532.4  956.17   542.4  960.21
#Mann= 3 , 0 , 0
       0      .1       0   233.6    .045       0   248.6      .1       0
Bank Sta=233.6,248.6
XS Rating Curve= 0 ,0
Exp/Cntr=0.3,0.1

Type RM Length L Ch R = 1 ,12723.8 ,391.5,399.2,406.9
XS GIS Cut Line= 2
     1605651.247      306666.224     1605214.377      306793.394
#Sta/Elev= 30
       0  938.53    10.1  938.53    20.2  931.99    30.3  923.85    40.4  913.05
    50.6  906.68    60.7  901.06   101.1  880.37   111.2  870.81   131.4  860.79
   171.9  843.23     182  836.43   192.1  830.63   212.3  820.49   222.4  817.01
   225.1  816.88   232.6   816.5   240.1  818.22   242.7  818.82   252.8   824.3
   262.9  831.15   283.1  840.23   303.3  848.51   323.6  857.59   333.7  866.67
   343.8  871.31   394.3  897.71   404.4  906.53   414.6  913.32     455  935.08
#Mann= 3 , 0 , 0
       0      .1       0   225.1    .045       0   240.1      .1       0
Bank Sta=225.1,240.1
XS Rating Curve= 0 ,0
Exp/Cntr=0.3,0.1

Type RM Length L Ch R = 1 ,12324.6 ,366.1,366.9,367.7
XS GIS Cut Line= 2
     1605595.258      306354.839     1605140.881      306331.032
#Sta/Elev= 30
    10.1     922    20.2  916.06    30.3  910.78    70.8  890.68    80.9  884.22
      91  876.86   111.2  867.59   151.7  850.33   161.8  842.47   171.9  837.63
   192.1  829.13   202.2  824.43   212.3  819.15   220.9 815.702   222.4   815.1
   232.6  815.14   235.9 816.339   242.7  818.81   262.9  827.96   293.2  839.73
   303.3  844.51   313.4  851.28   333.7  860.99   343.8  866.61   374.1   885.1
   384.2  896.11   394.3  903.75   414.6  916.57   444.9   936.6     455  948.08
#Mann= 3 , 0 , 0
    10.1      .1       0   220.9    .045       0   235.9      .1       0
Bank Sta=220.9,235.9
XS Rating Curve= 0 ,0
Exp/Cntr=0.3,0.1

Type RM Length L Ch R = 1 ,11957.7 ,298.8,298.7,298.5
XS GIS Cut Line= 2
     1605645.194      306001.399     1605184.463      305964.664
#Sta/Elev= 30
       0  935.91      10  935.91    20.1  930.59    30.1  920.12    90.4  887.83
   100.5  877.82   110.5  871.88   160.8  845.55   170.8  837.98   180.9  830.84
   190.9   825.3     211  815.44     221  811.85   231.1  810.42   243.7  810.15
   251.2  810.02   258.7  810.48   261.2  810.63   271.3  813.75   291.4  824.85
   301.4  829.59   311.5  834.05   321.5  841.45   331.6  847.77   351.7  857.12
   361.7  862.12   371.8  867.54   391.9  879.04     412  896.82   462.2  926.99
#Mann= 3 , 0 , 0
       0      .1       0   243.7    .045       0   258.7      .1       0
Bank Sta=243.7,258.7
XS Rating Curve= 0 ,0
Exp/Cntr=0.3,0.1

Type RM Length L Ch R = 1 ,11659   ,94,92.8,91.6
XS GIS Cut Line= 2
     1605751.142      305715.284     1605220.301       305700.35
#Sta/Elev= 30
      10  906.84      20  904.25    60.1  896.53    70.1   893.8    80.2  889.99
    90.2  882.66   100.2  874.59   120.2  866.26   150.3  855.64   170.3  846.94
   200.4  838.35   220.4  831.24   230.5  826.01   240.5  819.19   250.5  815.69
   260.5  813.14   270.5  812.02   300.6   810.4   320.6  808.46   337.2 808.165
   350.7  807.95   352.2 808.142   360.7  809.23   370.7  813.64   380.8  819.61
   390.8  828.49   450.9  854.34   460.9  863.09     491  877.02   531.1  897.16
#Mann= 3 , 0 , 0
      10      .1       0   337.2    .045       0   352.2      .1       0
Bank Sta=337.2,352.2
XS Rating Curve= 0 ,0
Exp/Cntr=0.3,0.1

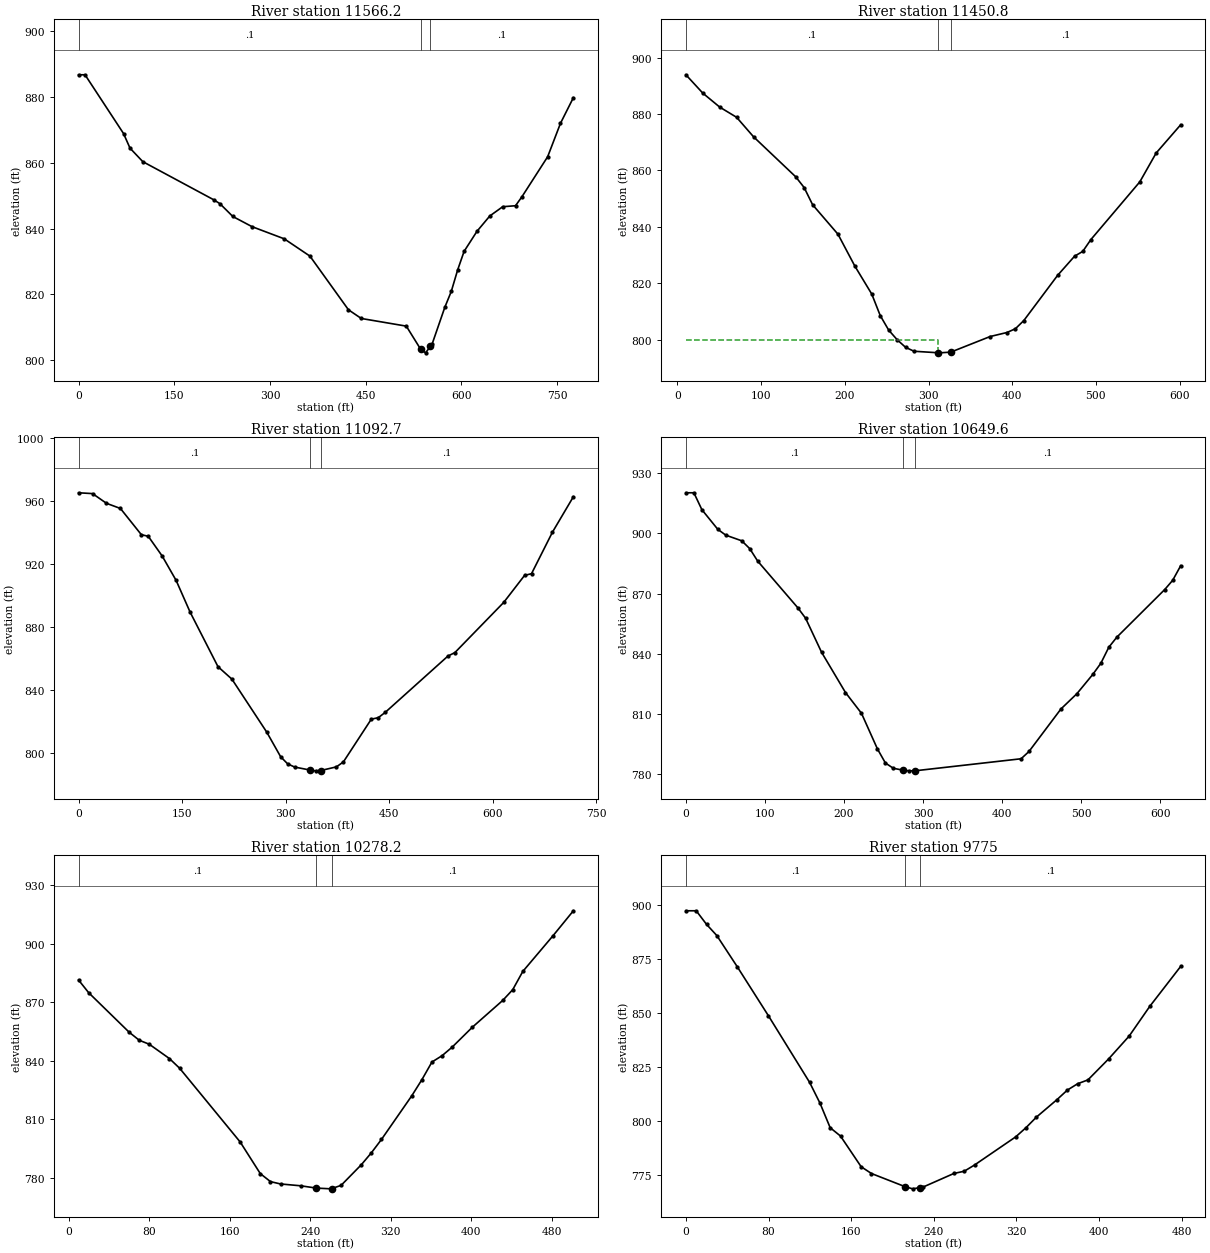
Type RM Length L Ch R = 1 ,11566.2 ,128.5,115.4,102
XS GIS Cut Line= 2
     1605949.754       305598.95     1605174.321      305618.691
#Sta/Elev= 30
       0  886.79    10.1  886.79    70.5  868.91    80.6  864.48   100.7  860.37
   211.6  848.81   221.6  847.59   241.8   843.7     272   840.6   322.4  836.91
   362.7  831.65   423.1  815.33   443.2  812.69   513.8  810.36   536.5  803.26
     544  802.24   551.5  804.17   554.1  804.83   574.2  816.11   584.3  820.92
   594.4  827.52   604.4   833.1   624.6   839.2   644.7  843.86   664.9  846.67
     685  846.97   695.1  849.71   735.4  861.87   755.5  872.04   775.7  879.83
#Mann= 3 , 0 , 0
       0      .1       0   536.5    .045       0   551.5      .1       0
Bank Sta=536.5,551.5
XS Rating Curve= 0 ,0
Exp/Cntr=0.3,0.1

Type RM Length L Ch R = 1 ,11450.8 ,369,358.1,347.6
XS GIS Cut Line= 3
     1605690.048      305322.924     1605290.899      305579.519
     1605165.995      305601.242
#Sta/Elev= 30
    10.1  893.88    30.3  887.37    50.5  882.42    70.7   878.8    90.9   871.9
   141.3  857.71   151.4  853.89   161.5   847.8   191.8  837.35     212  826.03
   232.2  816.12   242.3  808.51   252.4  803.35   262.5  799.95   272.6  797.24
   282.7  795.85   311.5 795.316     313  795.29   326.5 795.532   373.6  801.07
   393.7   802.5   403.8  803.83   413.9  806.75   454.3  822.78   474.5  829.55
   484.3  831.26     494  835.45   552.5  855.92     572  866.14   601.3  876.15
#Mann= 3 , 0 , 0
    10.1      .1       0   311.5    .045       0   326.5      .1       0
#XS Ineff= 2 , 0
       0     311     800               0
Permanent Ineff=
       F       F
Bank Sta=311.5,326.5
XS Rating Curve= 0 ,0
Exp/Cntr=0.3,0.1

Type RM Length L Ch R = 1 ,11092.7 ,435.3,443.1,450.9
XS GIS Cut Line= 2
     1605299.595      305009.743     1604957.585      305639.584
#Sta/Elev= 30
       0  965.24    20.2  964.72    40.4  958.56    60.6  955.29    90.9  938.67
   100.9  937.66   121.1  925.13   141.3  909.66   161.5   889.6   201.9  854.98
   222.1  847.07   272.6  813.43   292.7  797.85   302.8  793.37   312.9  791.33
   335.7   789.4   343.2  788.93   350.7  789.12   373.5  791.45   383.6   794.6
     424  821.69   434.1  822.63   444.2  826.01     535   861.7   545.1  863.92
   615.8  895.72     646  912.84   656.1  913.95   686.4  940.27   716.7  962.73
#Mann= 3 , 0 , 0
       0      .1       0   335.7    .045       0   350.7      .1       0
Bank Sta=335.7,350.7
XS Rating Curve= 0 ,0
Exp/Cntr=0.3,0.1

Type RM Length L Ch R = 1 ,10649.6 ,370.8,371.4,372
XS GIS Cut Line= 2
      1604971.13       304904.77     1604503.828      305321.278
#Sta/Elev= 30
       0  920.17    10.1  920.17    20.2  911.77    40.4  901.96    50.5  899.07
    70.7  896.26    80.8  892.35    90.9  886.12   141.4  863.02   151.4  857.76
   171.6  840.82   201.9  820.75   222.1  810.44   242.3   792.7   252.4  785.67
   262.5  783.03   275.2  782.08   282.7  781.77   290.2  781.81   424.1  787.78
   434.1  791.41   474.5  812.56   494.7  820.17   514.9  829.81     525  835.31
   535.1   843.3   545.2  848.29   605.8     872   615.9  876.61     626  883.85
#Mann= 3 , 0 , 0
       0      .1       0   275.2    .045       0   290.2      .1       0
Bank Sta=275.2,290.2
XS Rating Curve= 0 ,0
Exp/Cntr=0.3,0.1

Type RM Length L Ch R = 1 ,10278.2 ,507.4,503.2,498.9
XS GIS Cut Line= 2
      1604734.01       304655.52     1604351.448      304979.267
#Sta/Elev= 30
      10  881.44      20  874.95    60.1  854.74    70.2  850.58    80.2  848.52
   100.2  841.18   110.3  836.23   170.4  798.43   190.4   782.2   200.5   778.1
   210.5   776.9   230.5  775.96   246.1 774.783   260.6   774.4   261.1 774.489
   270.6  776.18   290.7  786.76   300.7   792.9   310.7  799.73   340.8  822.12
   350.8  830.34   360.8  839.41   370.9  842.68   380.9  847.06   400.9  857.25
     431  870.96     441   876.5     451  885.85   481.1  904.22   501.2  916.95
#Mann= 3 , 0 , 0
      10      .1       0   246.1    .045       0   261.1      .1       0
Bank Sta=246.1,261.1
XS Rating Curve= 0 ,0
Exp/Cntr=0.3,0.1

Type RM Length L Ch R = 1 ,9775    ,340.3,341.3,342.3
XS GIS Cut Line= 2
     1604405.627      304251.225     1604104.252      304623.712
#Sta/Elev= 30
       0  897.27      10  897.27      20  890.96    29.9  885.81    49.9   871.2
    79.9  848.61   119.8  817.72   129.8  808.14   139.7  796.72   149.7  792.85
   169.7  778.62   179.7  775.48   212.1  769.41   219.6  768.38   227.1  768.99
   229.6  769.19   259.5  775.51   269.5  776.54   279.5  779.43   319.4  792.49
   329.4  796.77   339.4  801.62   359.4  809.76   369.3  814.13   379.3  817.09
   389.3  818.88   409.3  828.59   429.2  839.18   449.2  852.98   479.1  871.48
#Mann= 3 , 0 , 0
       0      .1       0   212.1    .045       0   227.1      .1       0
Bank Sta=212.1,227.1
XS Rating Curve= 0 ,0
Exp/Cntr=0.3,0.1

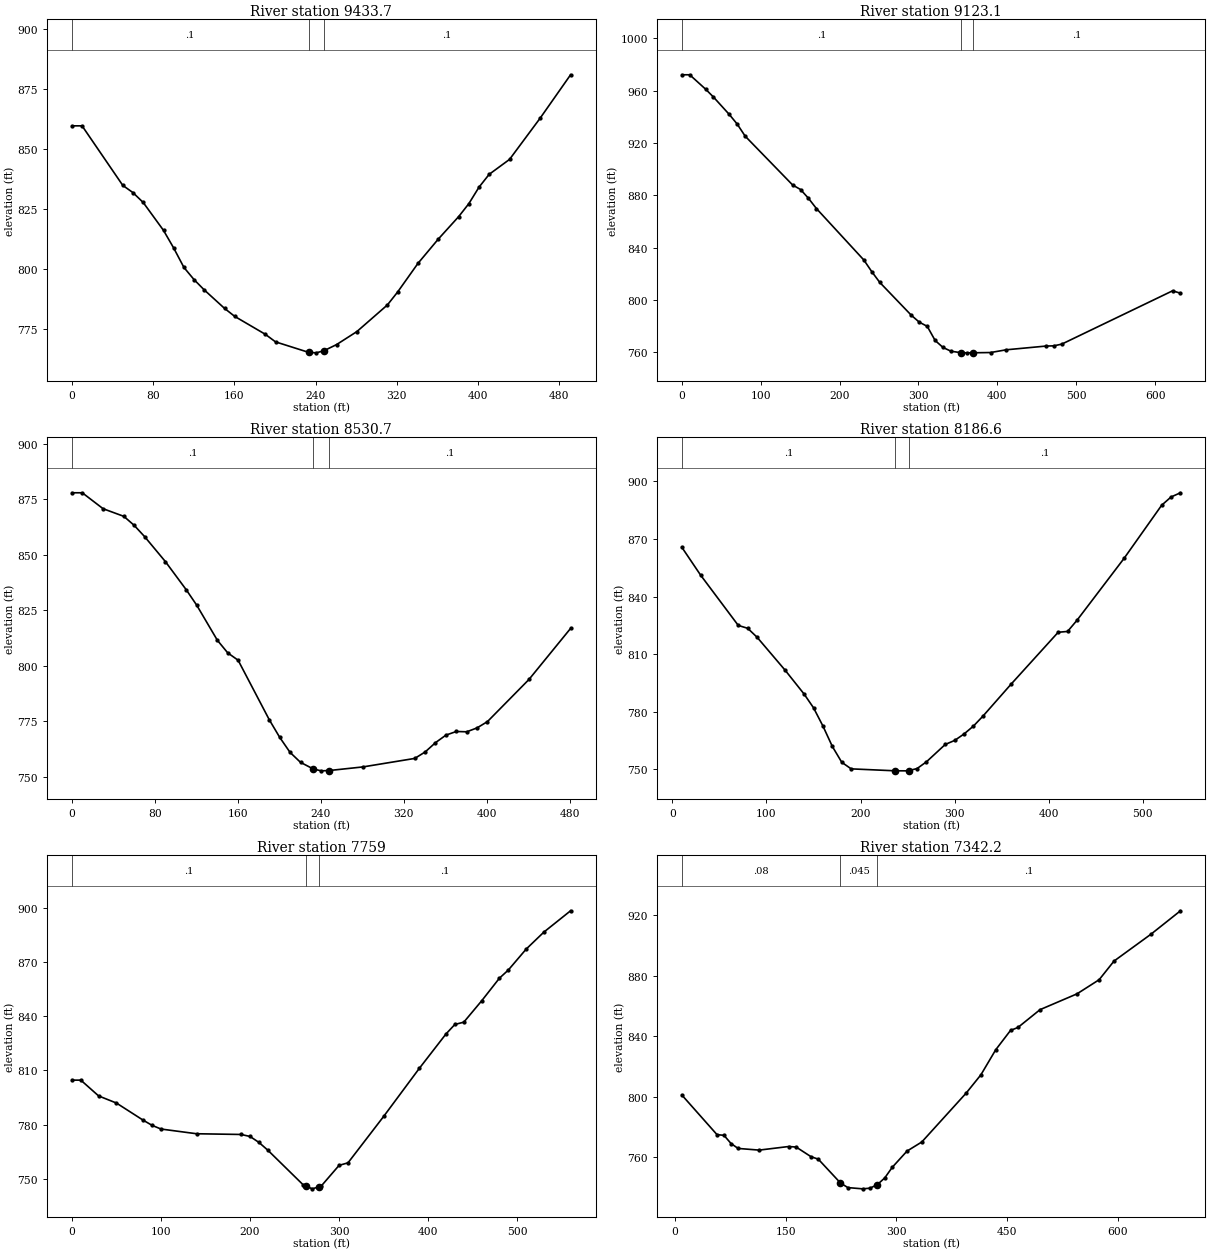
Type RM Length L Ch R = 1 ,9433.7  ,304.4,310.6,316.8
XS GIS Cut Line= 2
     1604146.264       304087.89     1603823.194      304457.786
#Sta/Elev= 30
       0  859.69      10  859.69    50.1  834.86    60.1  831.85    70.2  827.74
    90.2   816.1   100.2  808.77   110.3  800.66   120.3  795.56   130.3  791.29
   150.3  783.58   160.4  780.22   190.4  772.79   200.5  769.62     233  765.26
   240.5  765.04     248  765.88   260.6  768.47   280.6  773.89   310.7  785.01
   320.7  790.36   340.8  802.34   360.8  812.46   380.9  821.85   390.9  827.24
   400.9   834.1   410.9  839.46     431   845.7   461.1  862.87   491.1  880.98
#Mann= 3 , 0 , 0
       0      .1       0     233    .045       0     248      .1       0
Bank Sta=233,248
XS Rating Curve= 0 ,0
Exp/Cntr=0.3,0.1

Type RM Length L Ch R = 1 ,9123.1  ,621.7,592.5,563.2
XS GIS Cut Line= 2
     1604111.024      303827.945     1603579.384      304169.956
#Sta/Elev= 30
       0  972.22      10  972.22    30.1  961.25    40.1   955.2    60.2  941.86
    70.2  934.53    80.3  925.29   140.5  887.93   150.5  884.49   160.5  877.79
   170.6  869.96   230.8  830.54   240.8  821.66   250.9  813.47     291  788.28
     301  783.06   311.1  779.86   321.1  769.06   331.1   763.7   341.2  760.84
   353.7  759.72   361.2   759.6   368.7  759.64   391.3  759.83   411.4  761.94
   461.6  764.78   471.6  764.95   481.6  766.26   622.1  807.04   632.1  805.18
#Mann= 3 , 0 , 0
       0      .1       0   353.7    .045       0   368.7      .1       0
Bank Sta=353.7,368.7
XS Rating Curve= 0 ,0
Exp/Cntr=0.3,0.1

Type RM Length L Ch R = 1 ,8530.7  ,343.8,344,344.3
XS GIS Cut Line= 2
     1603216.411      303773.846     1603356.249      304234.089
#Sta/Elev= 30
       0  877.94      10  877.94    30.1  870.75    50.1  867.31    60.1  863.24
    70.1  858.19    90.2   846.9   110.2  834.27   120.3  827.33   140.3  811.45
   150.3  805.77   160.3  802.46   190.4   775.6   200.4  767.71   210.4  760.92
   220.5  756.42     233  753.39   240.5  752.59     248  752.72   280.6  754.35
   330.7  758.19   340.7  761.09   350.7  765.29   360.8   768.7   370.8  770.33
   380.8  770.19   390.8  771.95   400.8  774.78   440.9   793.8     481  816.79
#Mann= 3 , 0 , 0
       0      .1       0     233    .045       0     248      .1       0
Bank Sta=233,248
XS Rating Curve= 0 ,0
Exp/Cntr=0.3,0.1

Type RM Length L Ch R = 1 ,8186.6  ,433.8,427.6,421.4
XS GIS Cut Line= 2
     1602915.681      303905.829     1603068.062      304423.924
#Sta/Elev= 30
      10  865.75      30  851.21      70  825.03      80  823.53      90  818.87
     120  801.58     140  789.26     150  782.11     160   772.6     170  761.97
     180  753.73     190  750.31   236.5   749.3     250  749.28   251.5 749.456
     260  750.45     270  753.98     290  763.03     300  765.12     310   768.5
     320  772.62     330  777.75     360  794.45     410  821.46     420  821.89
     430   827.7     480  859.93     520  887.63     530  891.94     540  894.12
#Mann= 3 , 0 , 0
      10      .1       0   236.5    .045       0   251.5      .1       0
Bank Sta=236.5,251.5
XS Rating Curve= 0 ,0
Exp/Cntr=0.3,0.1

Type RM Length L Ch R = 1 ,7759    ,418.2,416.9,415.5
XS GIS Cut Line= 2
     1602458.538      304098.844     1602756.528      304572.918
#Sta/Elev= 30
       0  804.59      10  804.59      30  795.85      50  791.91      80  782.43
      90  779.58     100  777.54     140  774.93     190  774.53     200  773.43
     210  770.13     220  765.82     260   746.5   262.5  745.99     270  744.45
   277.5  745.64     280  746.04     300  757.45     310  758.84     350   784.5
     390  811.06     420  830.13     430  835.41     440  836.66     460  848.43
     480  860.99     490  865.51     510  877.07     530  886.53   559.9  898.29
#Mann= 3 , 0 , 0
       0      .1       0   262.5    .045       0   277.5      .1       0
Bank Sta=262.5,277.5
XS Rating Curve= 0 ,0
Exp/Cntr=0.3,0.1

Type RM Length L Ch R = 1 ,7342.2  ,549.9,566.6,583.4
XS GIS Cut Line= 3
     1602160.549       304346.04     1602184.253      304457.786
     1602516.104      304921.701
#Sta/Elev= 30
     9.5  801.21    57.1  774.98    66.6  774.49    76.2  769.05    85.7  765.83
   114.2  764.72   154.3  767.11   164.3  766.74   184.3   760.4   194.3  758.71
   224.3  742.96   234.3  739.91   254.3  739.09   264.3  739.53   274.3  741.92
   284.3  746.35   294.4  753.35   314.4  764.08   334.4   770.1   394.4  802.42
   414.4  814.55   434.5  831.15   454.5  843.93   464.5  845.87   494.5  857.68
   544.5  868.13   574.5  877.49   594.6  889.82   644.6  907.59   684.6  923.11
#Mann= 3 , 0 , 0
     9.5     .08       0   224.3    .045       0   274.3      .1       0
Bank Sta=224.3,274.3
XS Rating Curve= 0 ,0
Exp/Cntr=0.3,0.1

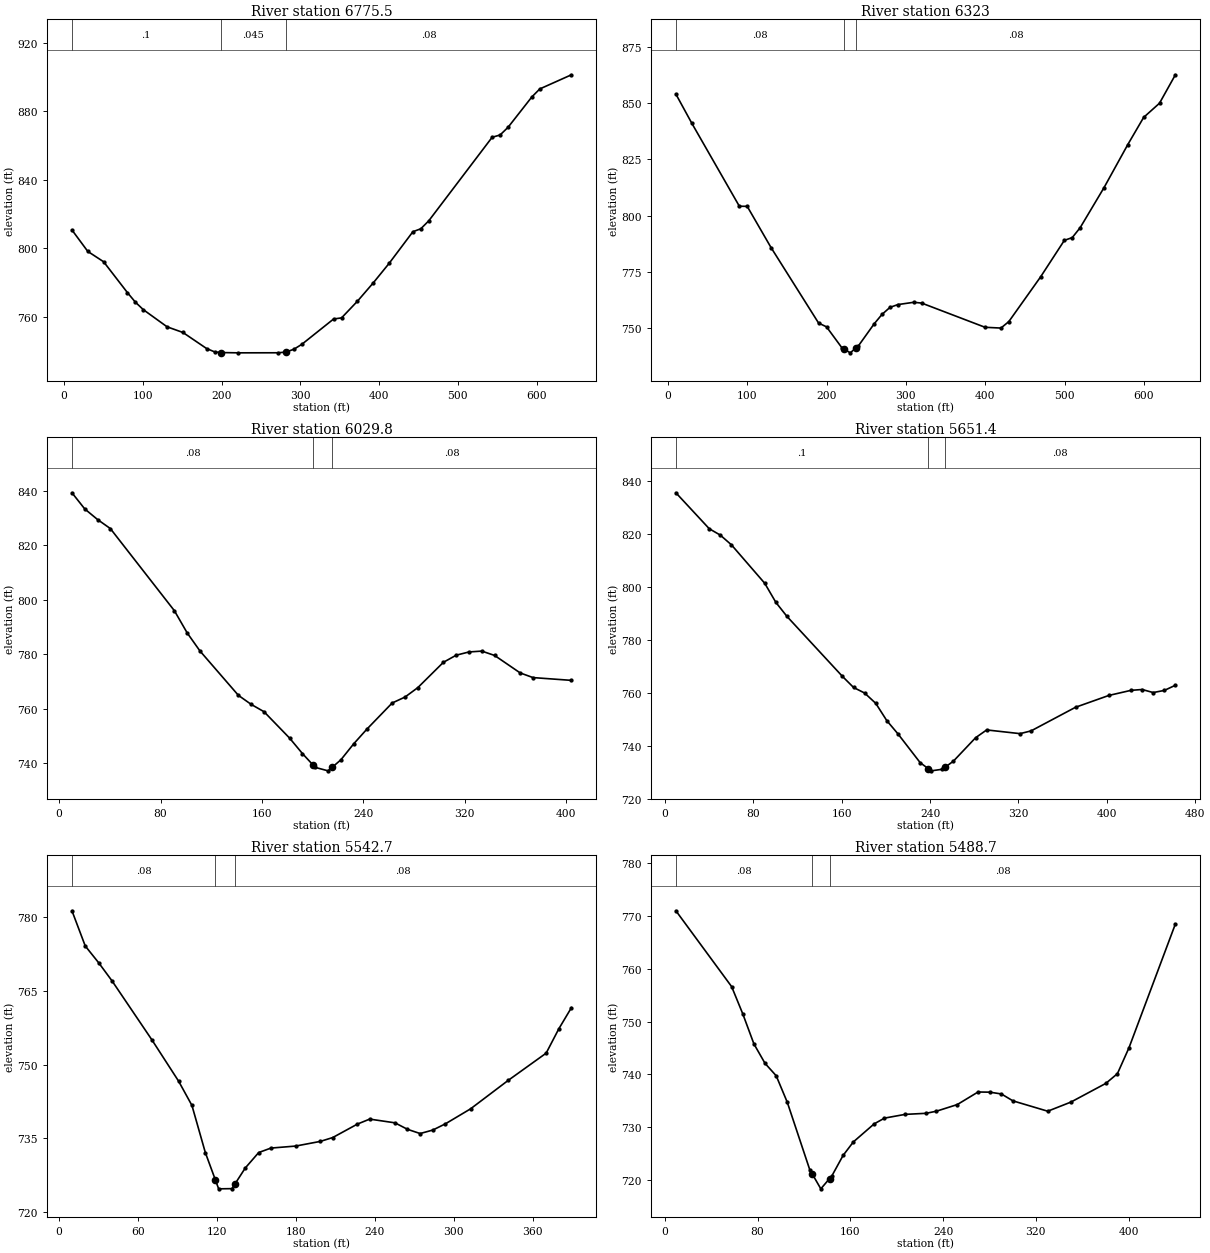
Type RM Length L Ch R = 1 ,6775.5  ,451.1,452.5,453.8
XS GIS Cut Line= 2
     1601737.269      304305.405     1601662.771      304945.405
#Sta/Elev= 30
    10.1  810.76    30.2  798.26    50.3  792.22    80.5  774.23    90.6  768.66
   100.7  764.27   130.9  754.26     151  750.96   181.2  741.55   191.3  739.64
   198.9 739.249   221.5  739.08   271.8  739.12   281.9  739.52     292  741.21
     302  744.06   342.3  758.82   352.4  759.47   372.5  769.16   392.6  779.86
   412.8  791.28     443  809.75     453  811.45   463.1  816.08   543.6  864.83
   553.7  866.18   563.8  870.65     594  888.36   604.1  893.04   644.3   901.3
#Mann= 3 , 0 , 0
    10.1      .1       0   198.9    .045       0   281.9     .08       0
Bank Sta=198.9,281.9
XS Rating Curve= 0 ,0
Exp/Cntr=0.3,0.1

Type RM Length L Ch R = 1 ,6323    ,281.7,293.3,304.9
XS GIS Cut Line= 2
     1601297.057      304302.019     1601185.311       304931.86
#Sta/Elev= 30
      10  853.93      30  841.04      90  804.15    99.9  804.11   129.9  785.83
   189.9  752.28   199.9   750.6   219.9  741.01   222.4  740.63   229.9  739.06
   237.4  741.42   239.9  742.06   259.9  751.91   269.9  756.15   279.9  759.25
   289.9  760.49   309.8   761.5   319.8  761.16   399.8   750.4   419.8  750.06
   429.8  752.97   469.8   772.8   499.7  788.99   509.7  790.24   519.7  794.65
   549.7  812.39   579.7  831.53   599.7   843.6   619.7   849.9   639.7  862.52
#Mann= 3 , 0 , 0
      10     .08       0   222.4    .045       0   237.4     .08       0
Bank Sta=222.4,237.4
XS Rating Curve= 0 ,0
Exp/Cntr=0.3,0.1

Type RM Length L Ch R = 1 ,6029.8  ,376.1,378.4,380.7
XS GIS Cut Line= 2
     1601131.132      304247.839     1600873.777      304559.373
#Sta/Elev= 30
    10.1  839.31    20.2  833.38    30.3  829.49    40.4  826.17    90.9  796.03
     101  787.88   111.1  781.24   141.4  764.97   151.5  761.65   161.6  758.97
   181.8  749.27   191.9  743.61   200.6 739.243     202  738.54   212.1  737.27
   215.6 738.665   222.2   741.3   232.3  747.16   242.5  752.45   262.7  762.17
   272.8  764.34   282.9   767.8   303.1   777.1   313.2  779.71   323.3   780.9
   333.4  781.21   343.5  779.61   363.7  773.19   373.8  771.49   404.1  770.47
#Mann= 3 , 0 , 0
    10.1     .08       0   200.6    .045       0   215.6     .08       0
Bank Sta=200.6,215.6
XS Rating Curve= 0 ,0
Exp/Cntr=0.3,0.1

Type RM Length L Ch R = 1 ,5651.4  ,107.6,108.7,109.7
XS GIS Cut Line= 2
     1600883.936      303997.257      1600555.47      304322.336
#Sta/Elev= 30
      10  835.41    40.2  821.84    50.2  819.43    60.3  815.75    90.4  801.26
   100.5  794.04   110.5  788.76   160.7  766.13   170.8  761.93   180.8  759.83
   190.9  755.94   200.9  749.41     211  744.41   231.1  733.55   238.6  731.23
   241.1  730.46   251.2  731.06   253.6 731.794   261.2  734.12   281.3  742.97
   291.3   745.9   321.5   744.5   331.5  745.54   371.7  754.45   401.9  758.92
   421.9  760.84     432  761.16     442  760.01   452.1  760.81   462.1  762.76
#Mann= 3 , 0 , 0
      10      .1       0   238.6    .045       0   253.6     .08       0
Bank Sta=238.6,253.6
XS Rating Curve= 0 ,0
Exp/Cntr=0.3,0.1

Type RM Length L Ch R = 1 ,5542.7  ,59.7,54,36.5
XS GIS Cut Line= 4
      1600745.49      303992.428     1600632.806      304094.251
     1600627.375      304178.426     1600535.055      304300.614
#Sta/Elev= 30
    10.1  781.34    20.2  774.17    30.4  770.75    40.5  767.08    70.9  755.02
    91.1  746.64   101.2  741.71   111.4  732.09     119 726.544   121.5  724.72
   131.6  724.76     134 725.758   141.7  728.96   151.9  732.11   161.2  733.02
     180  733.43   198.7  734.38   208.1  735.16   226.9  737.91   236.2  738.92
   255.4  738.16   264.9  736.84   274.5  735.98   284.1  736.69   293.7  737.96
   312.8  741.01   341.5  746.83   370.2  752.35   379.8   757.3   389.4  761.62
#Mann= 3 , 0 , 0
    10.1     .08       0     119    .045       0     134     .08       0
Bank Sta=119,134
XS Rating Curve= 0 ,0
Exp/Cntr=0.3,0.1

Type RM Length L Ch R = 1 ,5488.7  ,52.3,34.4,25
XS GIS Cut Line= 5
     1600691.239      303924.987     1600605.577      304052.716
     1600624.984      304102.623     1600621.543      304165.436
     1600501.114       304285.68
#Sta/Elev= 30
     9.6  771.01    57.7  756.63    67.3  751.47    76.9  745.78    86.5  742.09
    96.1  739.75   105.7  734.71     125  721.98   127.1  721.18   134.6  718.32
   142.1  720.26   144.2   720.8   153.8  724.65   162.7  727.22   180.6  730.63
   189.5  731.72   207.3  732.43   225.3  732.63   234.3  733.03   252.3  734.29
   270.2  736.67   280.3  736.64   290.3   736.3   300.3  734.99   330.3  733.03
   350.3  734.76   380.4   738.3   390.4  740.14   400.4  745.06   440.4  768.51
#Mann= 3 , 0 , 0
     9.6     .08       0   127.1    .045       0   142.1     .08       0
Bank Sta=127.1,142.1
XS Rating Curve= 0 ,0
Exp/Cntr=0.3,0.1

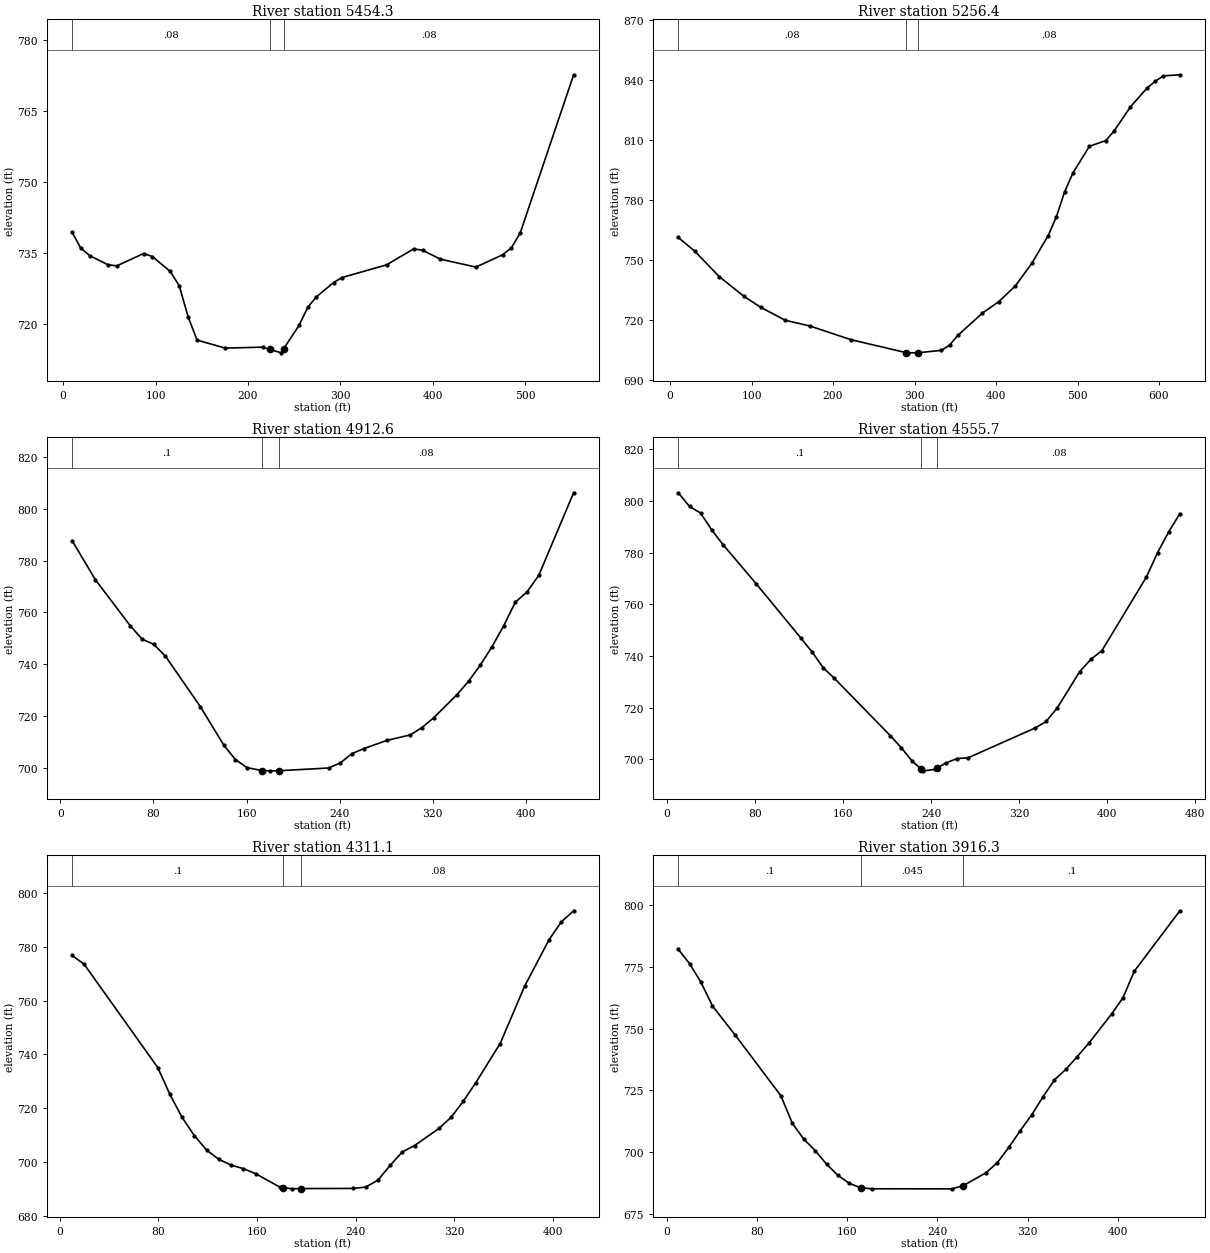
Type RM Length L Ch R = 1 ,5454.3  ,171.2,197.9,227.9
XS GIS Cut Line= 6
     1600650.703      303817.143     1600569.801      303937.378
     1600590.257      304036.408     1600615.519      304106.256
      1600613.99      304165.149     1600483.201      304278.346
#Sta/Elev= 30
     9.7  739.33    19.3  735.93      29  734.37    48.3  732.49      58  732.22
      87  734.83    96.6   734.2   115.9  731.05   125.6  728.04   135.3  721.44
   144.9  716.56   175.3  714.87   215.7  715.07   223.4 714.605   235.9  713.87
   238.4  714.69   255.3   719.7   264.6  723.47   273.9  725.67   292.5  728.71
   301.7  729.77   349.8  732.44   379.2  735.82   388.8  735.52   408.1  733.65
   446.5  731.97   475.3  734.56   484.9  736.04   494.5  739.22   552.2  772.57
#Mann= 3 , 0 , 0
     9.7     .08       0   223.4    .045       0   238.4     .08       0
#XS Ineff= 2 , 0
       0     174                       0
Permanent Ineff=
       F       F
Bank Sta=223.4,238.4
XS Rating Curve= 0 ,0
Exp/Cntr=0.3,0.1

Type RM Length L Ch R = 1 ,5256.4  ,356.9,343.8,330.7
XS GIS Cut Line= 2
     1600680.761      303763.606     1600166.053      304119.162
#Sta/Elev= 30
    10.1  761.33    30.3   754.5    60.5  741.75    90.8  731.91     111  726.54
   141.3     720   171.5  717.15     222  710.31   289.1 703.899   292.6  703.74
   304.1 703.785     333  704.97   343.1  707.64   353.1  712.43   383.4  723.62
   403.6  729.34   423.8  737.19     444  748.47   464.1  762.32   474.2  771.79
   484.3  784.26   494.4  793.54   514.6  806.86   534.8  809.73   544.9  814.52
     565  826.56   585.2  835.89   595.3   839.3   605.4  842.02   625.6  842.56
#Mann= 3 , 0 , 0
    10.1     .08       0   289.1    .045       0   304.1     .08       0
Bank Sta=289.1,304.1
XS Rating Curve= 0 ,0
Exp/Cntr=0.3,0.1

Type RM Length L Ch R = 1 ,4912.6  ,350,356.9,363.9
XS GIS Cut Line= 2
     1600247.233      303570.199     1600077.527      303977.494
#Sta/Elev= 30
      10  787.72    30.1  772.56    60.2  754.72    70.2  749.61    80.2  747.62
    90.3  743.01   120.3  723.53   140.4  708.69   150.4  703.07   160.4  699.99
     173  698.81   180.5  698.72     188  698.76   230.6  699.82   240.7   701.8
   250.7  705.39   260.7  707.29   280.8   710.5   300.8  712.61   310.9  715.47
   320.9  719.23     341   728.2     351  733.41     361  739.61     371   746.7
   381.1  754.81   391.1  763.91   401.1  767.87   411.2  774.25   441.2  806.19
#Mann= 3 , 0 , 0
      10      .1       0     173    .045       0     188     .08       0
Bank Sta=173,188
XS Rating Curve= 0 ,0
Exp/Cntr=0.3,0.1

Type RM Length L Ch R = 1 ,4555.7  ,242.2,244.6,247
XS GIS Cut Line= 2
     1600027.217       303391.12     1599725.841      303746.675
#Sta/Elev= 30
    10.1   803.2    20.3   797.9    30.4  795.33    40.5  788.83    50.7  783.16
    81.1  767.89   121.6  746.93   131.7   741.6   141.9  735.45     152  731.38
   202.7  709.23   212.8  704.52   222.9  699.19   230.5  696.45     233  695.55
   243.2  696.09   245.5 696.653   253.3  698.56   263.4  700.31   273.6   700.6
   334.4  712.11   344.5  714.66   354.6  719.89   374.9  733.86     385  738.66
   395.2  742.07   435.7  770.59   445.8  780.01     456  788.09   466.1  795.14
#Mann= 3 , 0 , 0
    10.1      .1       0   230.5    .045       0   245.5     .08       0
Bank Sta=230.5,245.5
XS Rating Curve= 0 ,0
Exp/Cntr=0.3,0.1

Type RM Length L Ch R = 1 ,4311.1  ,408.3,394.8,405.1
XS GIS Cut Line= 2
     1599834.508      303271.516      1599533.11      303559.338
#Sta/Elev= 30
     9.9  776.72    19.8  773.38    79.4  735.18    89.3  725.18    99.2  716.68
   109.1  709.96   119.1  704.56     129  701.17   138.9  699.02   148.8  697.73
   158.8  695.85   178.6  690.85     181   690.7   188.5  690.23     196  690.33
   238.1  690.38   248.1  690.88     258  693.43   267.9  698.89   277.8   703.9
   287.8  706.28   307.6  712.61   317.5  716.78   327.4  722.76   337.4  729.53
   357.2  744.07   377.1  765.36   396.9  782.55   406.8  789.11   416.8  793.24
#Mann= 3 , 0 , 0
     9.9      .1       0     181    .045       0     196     .08       0
Bank Sta=181,196
XS Rating Curve= 0 ,0
Exp/Cntr=0.3,0.1

Type RM Length L Ch R = 1 ,3916.3  ,438.2,444.7,448.5
XS GIS Cut Line= 2
     1599690.521      303005.606     1599261.843      303158.189
#Sta/Elev= 30
    10.1  782.15    20.2  776.28    30.3  768.73    40.4  759.21    60.7  747.33
   101.1  722.82   111.2   711.7   121.3   705.3   131.5   700.6   141.6  695.09
   151.7  690.56   161.8  687.31   171.9  685.51     182   685.1   252.8  685.08
   262.9  686.39   283.1   691.6   293.2  695.72   303.3   701.9   313.5   708.7
   323.6  715.08   333.7  722.44   343.8  729.24   353.9  733.54     364  738.68
   374.1  744.03   394.4  755.89   404.5  762.48   414.6  773.27     455  797.77
#Mann= 3 , 0 , 0
    10.1      .1       0   171.9    .045       0   262.9      .1       0
Bank Sta=171.9,262.9
XS Rating Curve= 0 ,0
Exp/Cntr=0.3,0.1