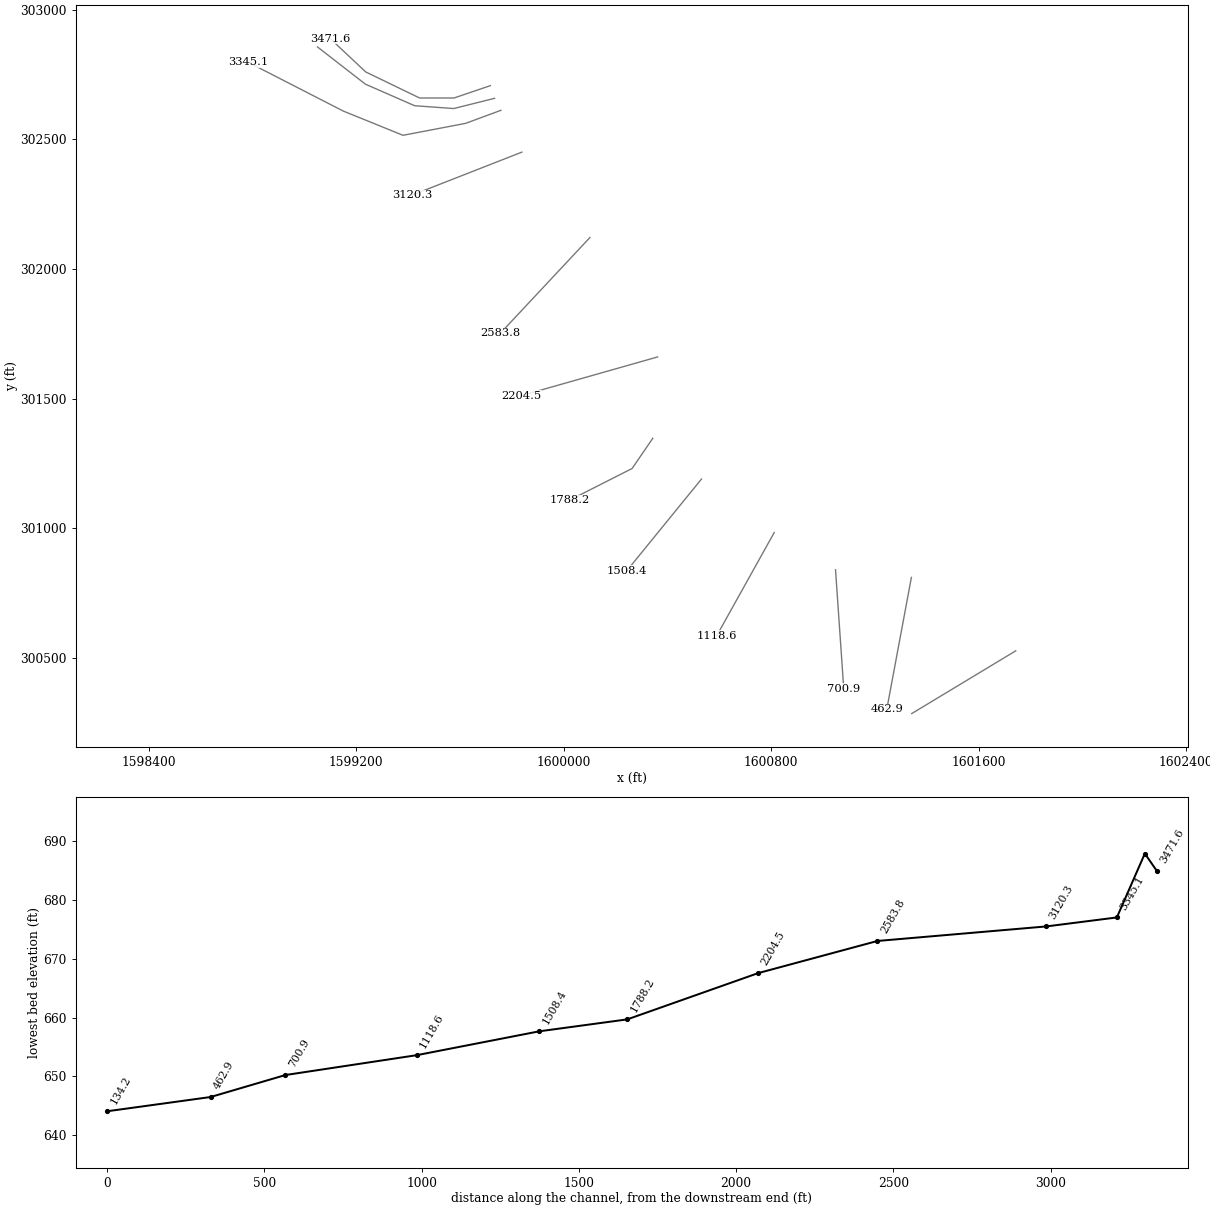
HEC-RAS study sprcfrk.prj: sprcfrk

--- sprcfrk.g01 (geometry) --- (continued)

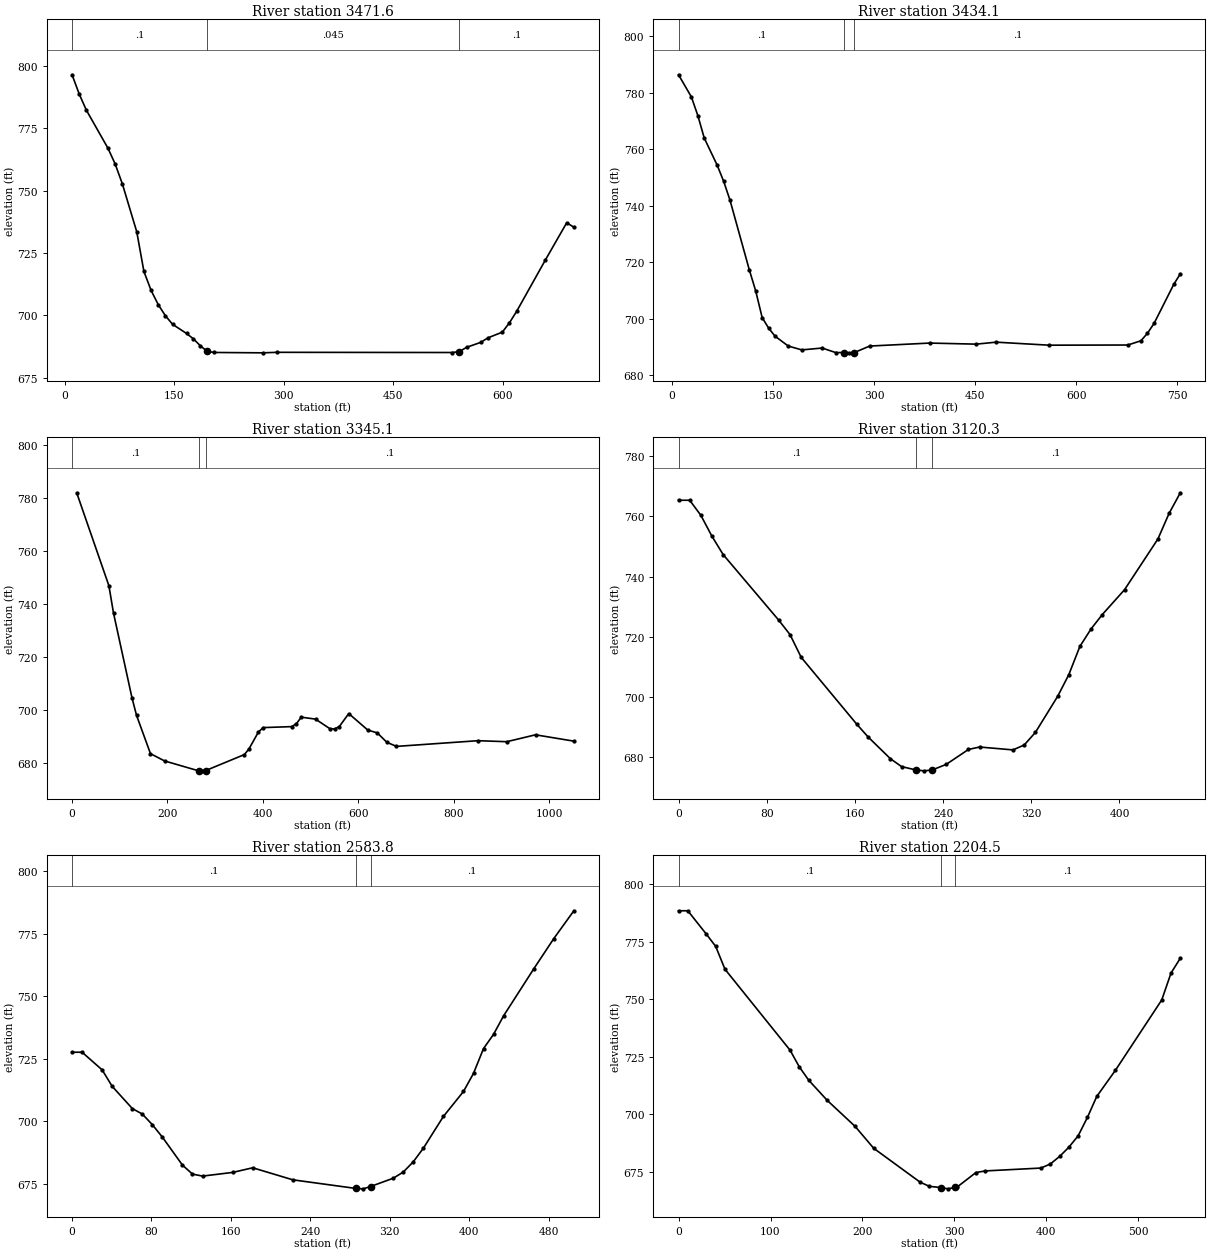
Type RM Length L Ch R = 1 ,3471.6  ,38.1,37.5,39.6
XS GIS Cut Line= 5
      1599717.75      302706.734     1599577.913      302659.217
     1599444.863      302659.217     1599237.143      302759.683
     1599101.378      302887.302
#Sta/Elev= 30
     9.8  796.35    19.7  788.56    29.5  782.12    59.1  766.89    68.9  760.61
    78.8  752.62    98.5  733.46   108.3  717.58   118.2  709.97     128  704.27
   137.8  699.83   147.7  696.39   166.7  692.76   176.2  690.58   185.7  687.82
   195.2  685.56   204.7  685.14   271.2  684.99   290.8   685.2   531.1  685.12
   540.9   685.5   550.7   687.2   570.3   689.2   580.1  691.01   599.7  693.28
   609.5  697.03   619.4  701.63   658.6   722.1     688  737.08   697.8  735.31
#Mann= 3 , 0 , 0
     9.8      .1       0   195.2    .045       0   540.9      .1       0
Bank Sta=195.2,540.9
XS Rating Curve= 0 ,0
Exp/Cntr=0.3,0.1

Type RM Length L Ch R = 1 ,3434.1  ,84.5,89,95.2
XS GIS Cut Line= 5
     1599734.042      302657.859     1599576.555      302618.487
     1599425.856      302629.348     1599235.938      302712.515
     1599051.145      302856.076
#Sta/Elev= 30
     9.5  786.38    28.6  778.53    38.2  771.91    47.7  763.96    66.8  754.41
    76.4  748.73    85.9     742   114.6  717.31   124.1  709.83   133.7   700.4
   143.2  696.69   152.8  693.81   172.4  690.31   192.6  688.94   222.8   689.6
   242.9     688   255.6     688   263.1   687.9   270.6     688   293.3   690.3
   382.5  691.36   451.6  690.98   481.3  691.68   559.8  690.61   676.8  690.67
   696.3  692.17     706  694.84   715.8  698.32     745  712.13   754.8  715.89
#Mann= 3 , 0 , 0
     9.5      .1       0   255.6    .045       0   270.6      .1       0
Bank Sta=255.6,270.6
XS Rating Curve= 0 ,0
Exp/Cntr=0.3,0.1

Type RM Length L Ch R = 1 ,3345.1  ,217.3,224.8,230.3
XS GIS Cut Line= 5
      1599758.48      302611.699     1599622.715      302561.466
     1599381.053      302515.306     1599150.253      302608.984
     1598783.573      302797.112
#Sta/Elev= 30
     9.7  781.91    77.2  746.86    86.9  736.52   125.5  704.66   135.1  697.98
   164.4   683.5     194  680.76   265.2  677.04   272.7  677.03   280.2  677.14
   361.3  683.17   371.1  685.36   390.8  691.72   400.8  693.34   460.5  693.71
   470.5  694.86   480.5  697.27   510.4  696.54   540.2  692.96   550.2   692.8
   560.2  693.73   580.1  698.63     620  692.41   639.9  691.34     660  687.79
   680.1  686.25     851   688.4   911.3  688.02   971.6  690.62    1052  688.23
#Mann= 3 , 0 , 0
       0      .1       0   265.2    .045       0   280.2      .1       0
Bank Sta=265.2,280.2
XS Rating Curve= 0 ,0
Exp/Cntr=0.3,0.1

Type RM Length L Ch R = 1 ,3120.3  ,526.4,536.5,546.6
XS GIS Cut Line= 2
     1599839.506      302450.506     1599415.687      302284.525
#Sta/Elev= 30
       0  765.34    10.1  765.34    20.2  760.37    30.3  753.39    40.5  747.29
      91  725.48   101.1  720.75   111.3  713.17   161.8  690.93     172  686.73
   192.2  679.53   202.3  676.91     215  675.82   222.5   675.5     230  675.77
   242.8  677.64     263   682.6   273.1  683.41   303.4  682.45   313.6  684.09
   323.7  688.25   343.9  700.22     354   707.4   364.1  716.82   374.2  722.61
   384.4  727.38   404.6  735.64   434.9   752.5     445  760.98   455.2  767.82
#Mann= 3 , 0 , 0
       0      .1       0     215    .045       0     230      .1       0
Bank Sta=215,230
XS Rating Curve= 0 ,0
Exp/Cntr=0.3,0.1

Type RM Length L Ch R = 1 ,2583.8  ,391.7,379.3,367.1
XS GIS Cut Line= 2
     1600101.714      302121.279     1599756.317      301752.179
#Sta/Elev= 30
       0  727.59    10.1  727.59    30.3  720.54    40.4  713.97    60.7  705.09
    70.8  702.89    80.9  698.64      91  693.67   111.2  682.51   121.3  678.92
   131.4  678.12   161.8  679.59     182  681.44   222.4  676.63   285.7   673.2
   293.2  673.03   300.7  673.96   323.5  677.26   333.6  679.72   343.7  683.81
   353.9  689.26   374.1  701.96   394.3  711.91   404.4  719.14   414.5  729.06
   424.6  734.73   434.7  742.12   465.1  760.89   485.3  772.99   505.5  784.08
#Mann= 3 , 0 , 0
       0      .1       0   285.7    .045       0   300.7      .1       0
Bank Sta=285.7,300.7
XS Rating Curve= 0 ,0
Exp/Cntr=0.3,0.1

Type RM Length L Ch R = 1 ,2204.5  ,412.2,416.3,420.7
XS GIS Cut Line= 2
     1600362.454       301660.75     1599837.587      301511.756
#Sta/Elev= 30
       0  788.51    10.1  788.51    30.3  778.32    40.4  773.02    50.5  763.08
   121.2  727.91   131.3  720.62   141.5  714.83   161.7  706.03     192  694.72
   212.2   685.2   262.7  670.45   272.8  668.64   285.5  668.11     293  667.56
   300.5  668.18   303.1   668.4   323.3  674.63   333.4  675.35     394   676.6
   404.2  678.36   414.3  681.63   424.4  685.67   434.5  690.62   444.6  698.64
   454.7  707.73   474.9  719.05   525.4  749.72   535.5  761.43   545.6  767.88
#Mann= 3 , 0 , 0
       0      .1       0   285.5    .045       0   300.5      .1       0
Bank Sta=285.5,300.5
XS Rating Curve= 0 ,0
Exp/Cntr=0.3,0.1

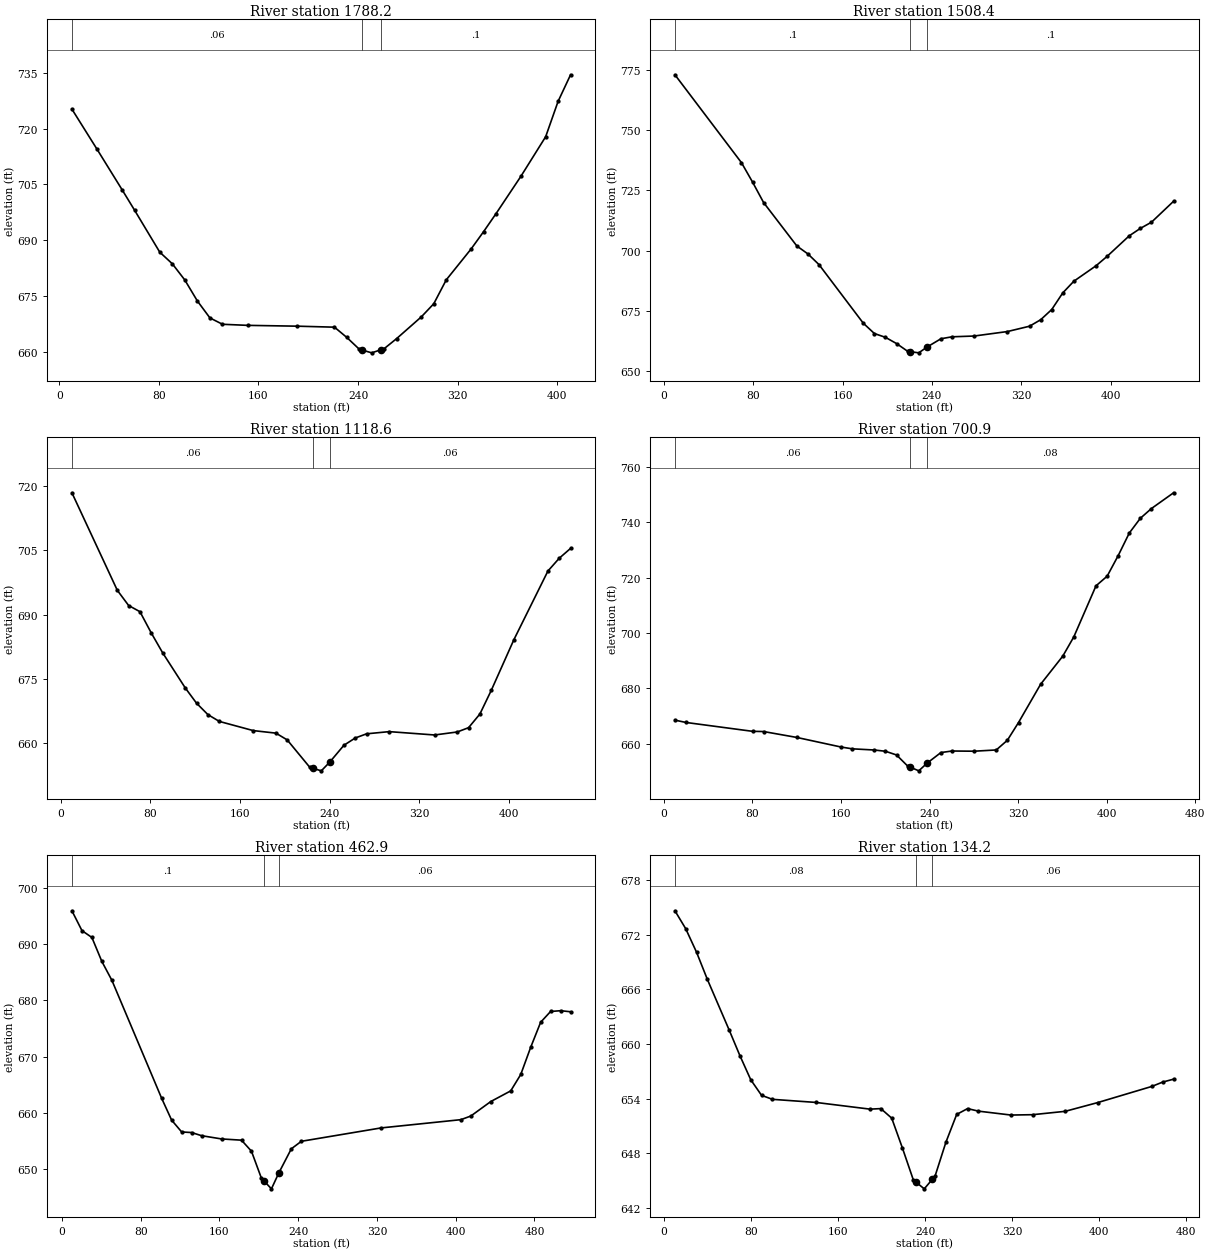
Type RM Length L Ch R = 1 ,1788.2  ,270.1,279.8,289.2
XS GIS Cut Line= 3
     1600344.021      301347.193     1600264.254      301230.698
      1600023.83      301108.793
#Sta/Elev= 30
    10.1  725.22    30.3  714.43    50.4  703.56    60.5  698.02    80.7  686.76
    90.8  683.63   100.8  679.29   110.9  673.64     121  669.08   131.1  667.37
   151.2  667.08   191.1  666.86   221.1  666.59     231  663.83     241  660.67
   243.5  660.42     251  659.69   258.5  660.53     261  660.81     271  663.51
   290.9  669.37   300.9   672.9   310.9  679.31   330.9  687.63   340.9  692.27
   350.8  697.07   370.8  707.11   390.8  717.81   400.8  727.33   410.8  734.46
#Mann= 3 , 0 , 0
    10.1     .06       0   243.5    .045       0   258.5      .1       0
Bank Sta=243.5,258.5
XS Rating Curve= 0 ,0
Exp/Cntr=0.3,0.1

Type RM Length L Ch R = 1 ,1508.4  ,385.8,389.7,393.7
XS GIS Cut Line= 2
     1600531.767      301190.063     1600243.638      300836.079
#Sta/Elev= 30
     9.9  772.97    69.5  736.51    79.4  728.48    89.3  719.98   119.1  701.96
     129  698.67   138.9  694.25   178.6  669.93   188.5  665.67   198.4  664.09
   208.4  661.49   218.3   658.3   220.7  658.14   228.2  657.66   235.7  660.08
   248.1   663.5     258  664.31   277.8  664.63   307.6  666.49   327.4   668.7
   337.4  671.39   347.3  675.62   357.2  682.53   367.1  687.36     387  693.78
   396.9  697.68   416.7  706.19   426.7  709.28   436.6  711.83   456.4  720.52
#Mann= 3 , 0 , 0
     9.9      .1       0   220.7    .045       0   235.7      .1       0
Bank Sta=220.7,235.7
XS Rating Curve= 0 ,0
Exp/Cntr=0.3,0.1

Type RM Length L Ch R = 1 ,1118.6  ,404.7,417.8,430.8
XS GIS Cut Line= 2
     1600812.249      300983.896     1600590.762      300586.443
#Sta/Elev= 30
    10.1  718.35    50.6  695.64    60.7   692.1    70.8  690.66    80.9  685.71
      91  681.11   111.2  672.92   121.3  669.35   131.4   666.7   141.6  665.11
   171.9  662.97   192.1  662.38   202.2   660.8   222.4   654.4   225.1  654.19
   232.6   653.6   240.1  655.62   252.8  659.56   262.9  661.25     273  662.22
   293.2  662.73   333.7  661.95   353.9  662.65     364  663.65   374.1  666.83
   384.2  672.31   404.4  684.12   434.8  700.13   444.9  703.11     455   705.4
#Mann= 3 , 0 , 0
    10.1     .06       0   225.1    .045       0   240.1     .06       0
Bank Sta=225.1,240.1
XS Rating Curve= 0 ,0
Exp/Cntr=0.3,0.1

Type RM Length L Ch R = 1 ,700.9   ,243.7,237.9,232.2
XS GIS Cut Line= 2
     1601048.543      300840.171     1601080.338      300380.751
#Sta/Elev= 30
      10  668.53      20  667.69    80.1  664.49    90.1  664.41   120.1  662.28
   160.2  658.81   170.2  658.17   190.2  657.74   200.2  657.29   210.2  655.95
   220.2  651.98   222.8  651.52   230.3  650.22   237.8  652.99   250.3  656.82
   260.3  657.38   280.3  657.31   300.3  657.76   310.3  661.24   320.4  667.65
   340.4   681.5   360.4  691.64   370.4  698.62   390.4  717.02   400.5  720.52
   410.5  727.97   420.5   736.1   430.5  741.43   440.5  744.94   460.5  750.63
#Mann= 3 , 0 , 0
      10     .06       0   222.8    .045       0   237.8     .08       0
Bank Sta=222.8,237.8
XS Rating Curve= 0 ,0
Exp/Cntr=0.3,0.1

Type RM Length L Ch R = 1 ,462.9   ,347.9,328.7,309.6
XS GIS Cut Line= 2
     1601341.079      300810.804     1601246.264      300302.867
#Sta/Elev= 30
    10.1  695.96    20.3  692.43    30.4  691.21    40.5  686.95    50.7  683.59
   101.3  662.58   111.4  658.71   121.6   656.6   131.7   656.5   141.8  655.94
   162.1  655.36   182.4  655.14   192.5  653.18   202.6  648.38   205.3  647.88
   212.8  646.48   220.3  649.31     233   653.6   243.2  654.94   324.2  657.32
   405.3  658.79   415.4  659.44   435.7  662.02   455.9  663.91   466.1  666.83
   476.2  671.67   486.3  676.12   496.4  678.04   506.6  678.18   516.7  677.99
#Mann= 3 , 0 , 0
    10.1      .1       0   205.3    .045       0   220.3     .06       0
Bank Sta=205.3,220.3
XS Rating Curve= 0 ,0
Exp/Cntr=0.3,0.1

Type RM Length L Ch R = 1 ,134.2   ,122.3,134.2,146
XS GIS Cut Line= 2
     1601743.362      300527.708     1601342.489      300285.885
#Sta/Elev= 30
      10  674.66    19.9  672.69    29.9  670.09    39.8  667.11    59.8  661.55
    69.7  658.72    79.7  656.06    89.6  654.35    99.6  653.91   139.5  653.57
   189.3  652.83   199.2  652.89   209.2  651.84   219.1  648.53   229.1  645.03
   231.6  644.79   239.1  644.06   246.6  645.12     249  645.45     259  649.19
   268.9  652.25   278.9  652.89   288.9  652.61   318.8  652.18   338.7  652.22
   368.6  652.59   398.4  653.55   448.2  655.33   458.2  655.81   468.2  656.13
#Mann= 3 , 0 , 0
      10     .08       0   231.6    .045       0   246.6     .06       0
Bank Sta=231.6,246.6
XS Rating Curve= 0 ,0
Exp/Cntr=0.3,0.1

Chan Stop Cuts=-1
Use User Specified Reach Order=0